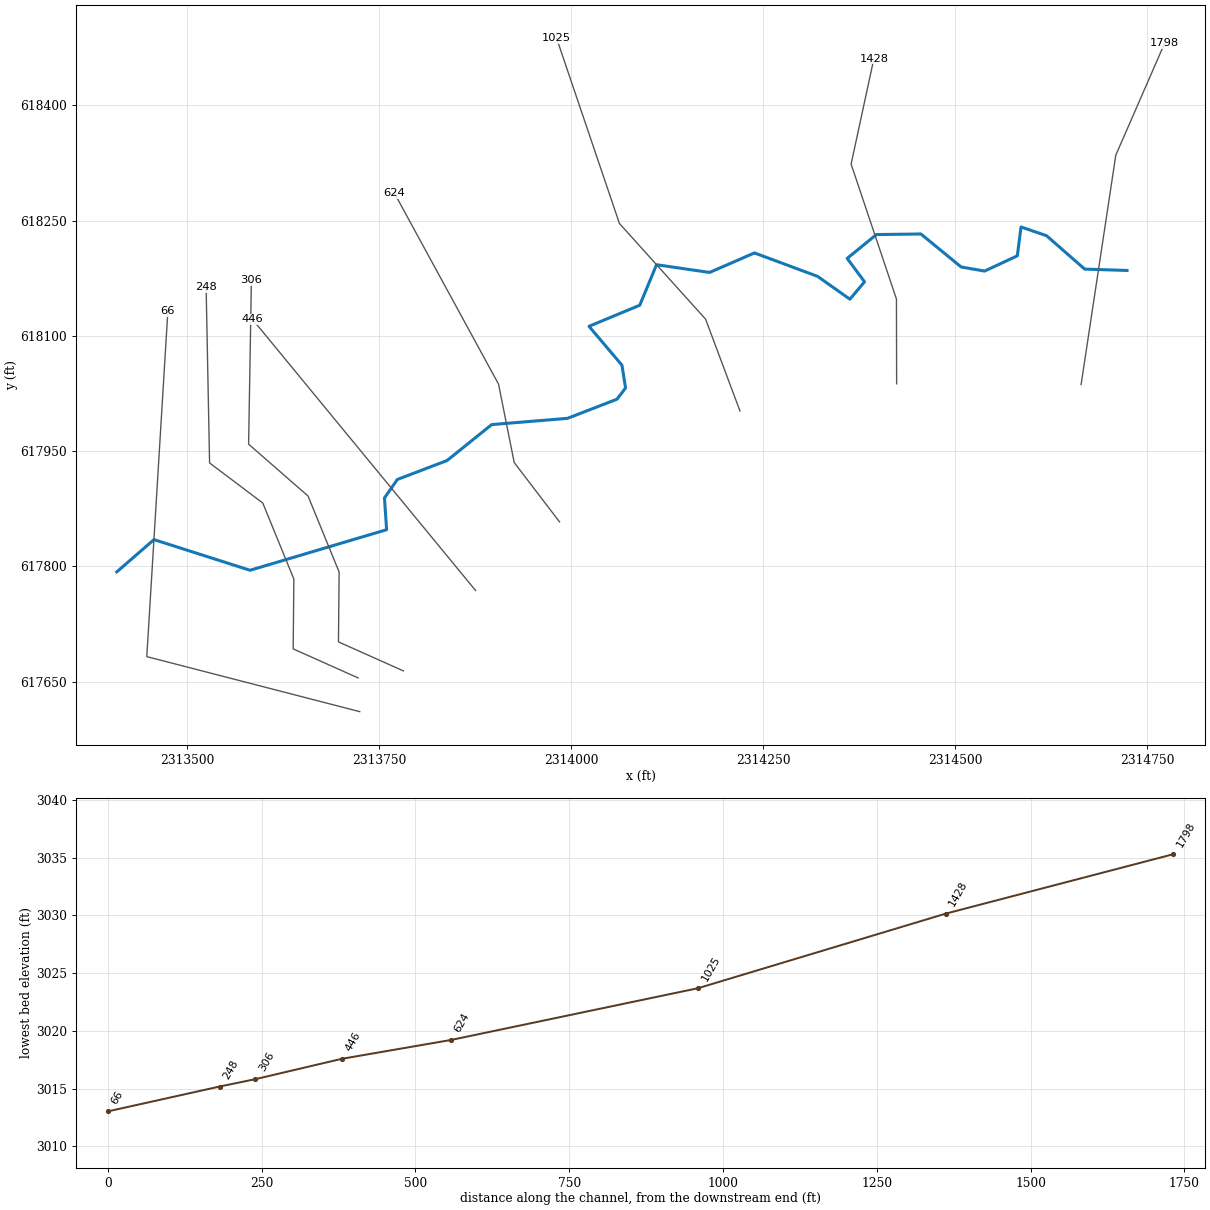
--- FOXRN.prj (project) ---

Proj Title=FOXRN
Current Plan=p01
Default Exp/Contr=0.3,0.1
English Units
Geom File=g01
Flow File=f01
Plan File=p01
Background Map Layer=Inundation Boundary (01pct Value_0)
Y Axis Title=Elevation
X Axis Title(PF)=Main Channel Distance
X Axis Title(XS)=Station
BEGIN DESCRIPTION:
----------MODEL BY WOOD PLC 2021----------
Stream Name: Fox Run
Flood Zone: Enhanced Approximate
Pocahontas County, WV
HEC-RAS Version: RAS 6.1
Vertical Datum: NAVD88
Projection: NAD 1983 StatePlane West Virginia S FIPS 4702 (US Feet)
Terrain: 1-meter LIDAR (FEMA Region III 3DEP collected 2016-2018)
Land Use: 2019 NLCD
Hydrologic Method:
WV SIR2010-5033 regression equations
Model Notes:
Normal depth tie in to West Fork Greenbrier River
END DESCRIPTION:
DSS Export Rating Curves= 0
DSS Export Rating Curve Sorted= 0
DSS Export Volume Flow Curves= 0
DXF OffsetX= 0
DXF OffsetY= 0
DXF ScaleX= 1
DXF ScaleY= 10

--- FOXRN.p01 (plan) ---

Plan Title=Floodplain
Program Version=6.10
Short Identifier=Floodplain
Geom File=g01
Flow File=f01
Subcritical Flow
K Sum by GR= 0
Std Step Tol= 0.01
Critical Tol= 0.01
Num of Std Step Trials= 20
Max Error Tol= 0.3
Flow Tol Ratio= 0.001
Split Flow NTrial= 30
Split Flow Tol= 0.02
Split Flow Ratio= 0.02
Log Output Level= 0
Friction Slope Method= 1
Unsteady Friction Slope Method= 2
Unsteady Bridges Friction Slope Method= 1
Parabolic Critical Depth
Global Vel Dist= 0 , 0 , 0
Global Log Level= 0
CheckData=True
Encroach Param=-1 ,0,0, 0
Computation Interval=1MIN
Output Interval=1HOUR
Instantaneous Interval=1HOUR
Mapping Interval=1HOUR
Computation Time Step Use Courant=        0
Computation Time Step Use Time Series=    0
Computation Time Step Count To Double=0
Computation Time Step Max Doubling=0
Computation Time Step Max Halving=0
Computation Time Step Residence Courant=0
Run HTab= 0
Run UNet= 0
Run Sediment= 0
Run PostProcess= 0
Run WQNet= 0
Run RASMapper=-1
UNET Theta= 1
UNET Theta Warmup= 1
UNET ZTol= 0.02
UNET ZSATol= 0.02
UNET MxIter= 20
UNET Max Iter WO Improvement= 0
UNET MaxInSteps= 0
UNET DtIC= 0
UNET DtMin= 0
UNET MaxCRTS= 20
UNET WFStab= 2
UNET SFStab= 1
UNET WFX= 1
UNET SFX= 1
UNET Gravity=32.174
UNET 1D Methodology=Finite Difference
UNET DSS MLevel= 4
UNET Pardiso=0
UNET DZMax Abort= 100
UNET Use Existing IB Tables=-1
UNET Froude Reduction=False
UNET Froude Limit= 0.8
UNET Froude Power= 4
UNET D1 Cores= 0
UNET WindReference=Eulerian
UNET WindDragFormulation=Hsu (1988)
UNET D2 Coriolis=0
UNET D2 Cores= 0
UNET D2 Theta= 1
UNET D2 Theta Warmup= 1
UNET D2 Z Tol= 0.01
UNET D2 Volume Tol= 0.01
UNET D2 Max Iterations= 20
UNET D2 Equation= 0
UNET D2 RampUpFraction=0.1
UNET D2 TimeSlices= 1
UNET D2 Turbulence Formulation=None
UNET D2 Eddy Viscosity=0.3
UNET D2 Transverse Eddy Viscosity=0.1
UNET D2 Smagorinsky Mixing=0.05
UNET D2 BCVolumeCheck=0
UNET D2 Cores=0
UNET D2 SolverType=PARDISO (Direct)
UNET D2 Minimum Iterations= 2147483647
UNET D2 Maximum Iterations= 2147483647
UNET D2 Restart Number= 10
UNET D2 Relaxation Coeff=1.3
UNET D2 SOR Precondition Iterations= 10
UNET D2 ILUT Maximum Fill= 8
UNET D2 ILUT Tolerance=1E-08
UNET D1D2 MaxIter= 0
UNET D1D2 ZTol=0.01
UNET D1D2 QTol=0.1
UNET D1D2 MinQTol=1
Write IC File= 0
Write IC File at Fixed DateTime=0
Write IC File at Sim End=0
Echo Input=False
Echo Parameters=False
Echo Output=False
Write Detailed= 0
HDF Write Warmup=0
HDF Write Time Slices=0
HDF Flush=0
HDF Compression= 1
HDF Chunk Size= 1
HDF Spatial Parts= 1
HDF Use Max Rows=0
HDF Fixed Rows= 1
Calibration Method= 0
Calibration Iterations= 20
Calibration Max Change=0.05
Calibration Tolerance=0.2
Calibration Maximum=1.5
Calibration Minimum=0.5
Calibration Optimization Method= 1
WQ AD Non Conservative
WQ ULTIMATE=-1
WQ Max Comp Step=1HOUR
WQ Output Interval=15MIN
WQ Output Selected Increments= 0
WQ Output face flow=0
WQ Output face velocity=0
WQ Output face area=0
WQ Output face dispersion=0
WQ Output cell volume=0
WQ Output cell surface area=0
WQ Output cell continuity=0
WQ Output cumulative cell continuity=0
WQ Output face conc=0
WQ Output face dconc_dx=0
WQ Output face courant=0
WQ Output face peclet=0
WQ Output face adv mass=0
WQ Output face disp mass=0
WQ Output cell mass=0
WQ Output cell source sink temp=0
WQ Output nsm pathways=0
WQ Output nsm derived pathways=0
WQ Create Restart=0
WQ Fixed Restart=0
WQ System Summary=0
WQ Write To DSS=0
Sorting and Armoring Iterations= 10
XS Update Threshold= 0.02
Bed Roughness Predictor= 0
Hydraulics Update Threshold= 0.02
Energy Slope Method= 1
Volume Change Method= 1
Sediment Retention Method= 0
Sediment TS Multiplier= 1
Warm Up Method= 0
XS Weighting Method= 0
Number of US Weighted Cross Sections= 1
Number of DS Weighted Cross Sections= 1
Upstream XS Weight=0
Main XS Weight=1
Downstream XS Weight=0
Number of DS XS's Weighted with US Boundary= 1
Upstream Boundary Weight= 1
Weight of XSs Associated with US Boundary= 0
Number of US XS's Weighted with DS Boundary= 1
Downstream Boundary Weight= 0.5
Weight of XSs Associated with DS Boundary= 0.5
Percentile Method= 0
Sediment Output Level= 3
Mass or Volume Output= 0
Output Increment Type= 1
Profile and TS Output Increment= 1
Transport Output Increment 1
XS Output Flag= 0
XS Output Increment= 10
Read HDF5 Sediment Hotstart= 0
Sediment Hotstart Type= 0
Write Gradation File= 0
Read Gradation Hotstart= 0
Write HDF5 File= 1
Write Binary Output= 1
Write DSS Sediment File= 0
DSS Sediment Output Type= 1
SV Curve= 0
Specific Gage Flag= 0
Subcell Erosion Methods= 0
Subcell Deposition Methods= 0
Advection Scheme= 1
Matrix Solver= 0
Implicit Weighting Factor= 1
Maximum Outer Loop Convergence Iterations= 5
Convergence Maximum Absolute= 0.001
Convergence RMSE= 0.0001
Grain Fractions Max Abs Error= 0.001
Max Subgrid Regions= 1
Max Subgrid Length Scale= 3.402823E+38
Initial Layer Thickness= 3.402823E+38
Min Layer Thickness= 3.402823E+38
Max Layer Thickness= 3.402823E+38
Number of Layers= 5

--- FOXRN.f01 (steady flow) ---

Flow Title=Flow
Program Version=6.10
Number of Profiles= 6
Profile Names=01pct,10pct,04pct,02pct,0_2pct,01plus
River Rch & RM=FOXRN,Main            ,1798
     498     262     349     421     697     737
Boundary for River Rch & Prof#=FOXRN,Main            , 1
Up Type= 0
Dn Type= 3
Dn Slope=0.01127
Boundary for River Rch & Prof#=FOXRN,Main            , 2
Up Type= 0
Dn Type= 3
Dn Slope=0.01127
Boundary for River Rch & Prof#=FOXRN,Main            , 3
Up Type= 0
Dn Type= 3
Dn Slope=0.01127
Boundary for River Rch & Prof#=FOXRN,Main            , 4
Up Type= 0
Dn Type= 3
Dn Slope=0.01127
Boundary for River Rch & Prof#=FOXRN,Main            , 5
Up Type= 0
Dn Type= 3
Dn Slope=0.01127
Boundary for River Rch & Prof#=FOXRN,Main            , 6
Up Type= 0
Dn Type= 3
Dn Slope=0.01127
DSS Import GetInterval= 0
DSS Import GetPeak= 0
DSS Import FillOption= 0

--- FOXRN.g01 (geometry) ---

Geom Title=Geometry
Program Version=6.10

River Reach=FOXRN           ,Main
Reach XY= 30
2314724.01860586618185.0570707172314668.84768347618186.791109487
 2314619.2409642618230.2344936882314585.95743999618241.667765379
 2314581.1300586618204.0650051532314538.44584429618184.247334212
2314507.95711975618189.5828610062314455.61814269618232.521148026
2314397.68956612618231.758929923 2314359.5786605618200.762059987
2314382.19113116618170.2733354872314363.13567834618147.660864815
2314320.95960943618177.3873712122314238.89412595618207.876095727
  2314180.457404618182.4688252812314111.36931762618192.491114825
2314089.49937588618139.7846109722314023.44047277618112.344758928
  2314066.304232618061.8099652382314071.03724991618032.121034697
2314059.85011664 618017.491706612313995.53287368617992.617060989
2313896.69990964617984.4405442482313838.67095865617937.703713477
2313773.91805252617913.036629647 2313757.1128848617888.972561046
2313759.93978733617847.6804219632313582.07727695617794.871559501
2313456.99652177617834.7579922682313408.56109991617792.748098621

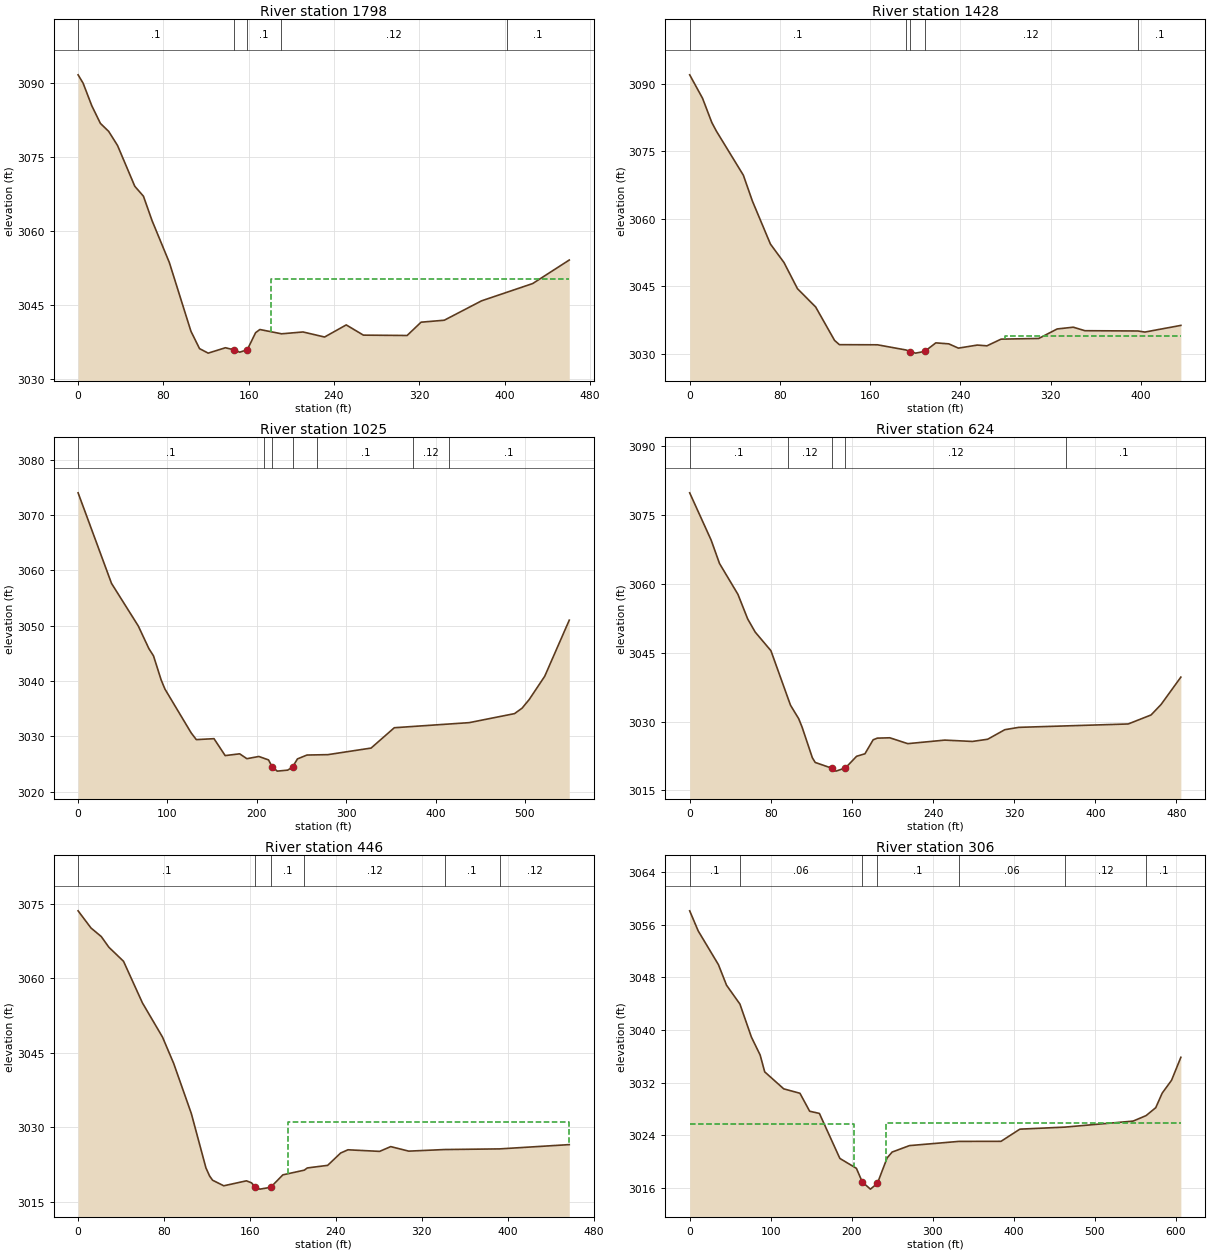
Type RM Length L Ch R = 1 ,1798    ,370.4,370.4,370.4
XS GIS Cut Line= 3
2314664.17539604618036.5563546152314709.37383569 618335.11698028
2314772.84597171 618480.58118844
#Sta/Elev= 30
       0 3091.62     4.7 3089.93    12.8 3085.38    20.9  3081.8    28.7 3080.17
      37 3077.32    53.2 3069.06    61.3 3067.05    69.4  3062.1    85.6 3053.63
   105.8 3039.75   113.9 3036.21     122  3035.3   138.2 3036.39 146.4913035.948
   151.6 3035.49158.69023035.989   166.5 3039.44   170.5 3040.08   190.8 3039.21
     211 3039.58   231.2 3038.56   251.5 3041.01   267.6 3038.94   308.6 3038.87
   321.7 3041.56   343.5 3041.96   378.4 3045.88   426.4 3049.38   460.7 3054.14
#Mann= 5 ,-1,0
       0      .1       0 146.491    .045       0158.6902      .1       0
     190     .12       0  401.96      .1       0
#XS Ineff= 2 , 0
                          181.06         3050.32
Permanent Ineff=
       F       F
Bank Sta=146.491,158.6902
XS Rating Curve= 0 ,0
Exp/Cntr(USF)=0,0
Exp/Cntr=0.3,0.1

Type RM Length L Ch R = 1 ,1428    ,394.9,402.4,397.1
XS GIS Cut Line= 4
2314423.98313938618037.5891073122314423.73386313618147.847916635
2314364.71131778618323.4582058892314394.29644533618460.399598318
#Sta/Elev= 30
       0 3091.97    11.4 3086.76    19.6 3081.39    23.6  3079.5    47.6 3069.67
    55.6 3063.94    71.6 3054.38    83.6 3050.29    95.6 3044.46   111.7 3040.41
   128.5 3032.97   132.8 3032.03   166.5    3032   191.8 3030.85   195.7  3030.5
   200.3 3030.15   208.4 3030.53   218.3 3032.43   229.8 3032.21   238.3 3031.26
   255.1 3031.94   263.6 3031.77   276.2 3033.26   309.6 3033.41   325.9 3035.52
   340.2 3035.91   350.5 3035.13   397.5 3035.07   403.7 3034.83   435.6 3036.31
#Mann= 5 ,-1,0
       0      .1       0   191.8     .12       0   195.7    .045       0
   208.4     .12       0   397.5      .1       0
#XS Ineff= 2 , 0
                             280            3034
Permanent Ineff=
       F       F
Bank Sta=195.7,208.4
XS Rating Curve= 0 ,0
Exp/Cntr(USF)=0,0
Exp/Cntr=0.3,0.1

Type RM Length L Ch R = 1 ,1025    ,407.4,401.5,396.4
XS GIS Cut Line= 4
2314219.98326103618002.1802956222314175.25623393618121.615674257
2314063.04053043618246.2188255532313981.25926013618487.243884005
#Sta/Elev= 30
       0 3074.04    37.4 3057.66    67.3 3049.97    79.3 3045.84    84.4 3044.55
    92.9 3040.22    97.2 3038.54   126.5 3030.63   132.3  3029.4   152.1 3029.57
   164.6 3026.51   180.8 3026.83   188.9 3025.95   202.3 3026.35   213.1 3025.73
   217.2 3024.48   222.9  3023.7   234.6 3023.88     240 3024.45   245.5 3025.91
   256.1 3026.61   279.5 3026.68   327.9 3027.87   353.9 3031.55   437.7 3032.47
   488.4  3034.1   496.9 3035.09   504.8 3036.64   522.2 3040.85   549.7 3051.01
#Mann= 7 ,-1,0
       0      .1       0  207.54     .12       0   217.2    .045       0
     240     .12       0  267.54      .1       0  375.22     .12       0
  415.22      .1       0
Bank Sta=217.2,240
XS Rating Curve= 0 ,0
Exp/Cntr(USF)=0,0
Exp/Cntr=0.3,0.1

Type RM Length L Ch R = 1 ,624     ,169.7,177.5,181.6
XS GIS Cut Line= 4
2313985.07247669617857.8359036752313926.04993134617935.075284011
2313905.64707616618037.0895599272313770.11382387618285.567189121
#Sta/Elev= 30
       0 3079.89    21.2 3069.56    29.4 3064.49    47.6 3057.75    57.2 3052.39
    64.6 3049.53    80.1 3045.47    99.4 3033.59   107.5 3030.64   110.8 3028.83
     121 3022.11   123.8 3021.11   140.1 3019.86   144.2 3019.22   153.6 3019.92
   164.6 3022.46   172.8    3023   180.9 3026.05     185 3026.41   197.3 3026.49
     215 3025.21   251.5 3025.98   278.8 3025.69   293.8 3026.17   310.7 3028.25
   324.4 3028.76   432.4  3029.5   454.9 3031.46   464.8 3033.75   484.3 3039.71
#Mann= 5 ,-1,0
       0      .1       0   97.21     .12       0   140.1    .045       0
   153.6     .12       0  371.24      .1       0
Bank Sta=140.1,153.6
XS Rating Curve= 0 ,0
Exp/Cntr(USF)=0,0
Exp/Cntr=0.3,0.1

Type RM Length L Ch R = 1 ,446     ,142.3,140.4,134.8
BEGIN DESCRIPTION:
Structure XS 4
END DESCRIPTION:
XS GIS Cut Line= 2
2313875.78703341617768.4854490852313585.21942833618121.509933486
#Sta/Elev= 30
       0 3073.55      12  3070.1    21.6 3068.37    28.6 3066.24    42.3  3063.4
    59.9 3055.03    78.6 3048.15      89 3042.85   105.4 3032.79     119 3021.86
   122.4 3020.23   125.2 3019.38   135.6 3018.26   156.7 3019.26   161.5 3018.85
     165 3017.95   169.3 3017.59   179.2 3017.95   190.6 3020.46   210.5  3021.4
   213.4 3021.85   232.3 3022.37   244.4 3024.85   251.2  3025.5   280.7 3025.18
     291 3026.14   307.8 3025.23   341.2 3025.55   392.4 3025.68   457.2 3026.54
#Mann= 6 ,-1,0
       0      .1       0     165    .045       0   179.2      .1       0
   210.5     .12       0   341.2      .1       0   392.4     .12       0
#XS Ineff= 2 , 0
                          195.18            3031
Permanent Ineff=
       F       F
Bank Sta=165,179.2
XS Rating Curve= 0 ,0
Exp/Cntr(USF)=0,0
Exp/Cntr=0.5,0.3

Type RM Length L Ch R = 1 ,306     ,58.1,58.2,58.1
BEGIN DESCRIPTION:
Structure XS 3; 9.8 ft between structure and xs
END DESCRIPTION:
XS GIS Cut Line= 6
2313781.76041922617663.8960287832313697.19832101617701.679093936
 2313698.0979178617792.5383696632313657.61606228617891.494016494
2313580.21970501617958.9692740332313583.84912555618172.168214779
#Sta/Elev= 30
       0  3058.1    10.5 3055.05    35.5 3049.92    45.5  3046.8      62 3043.94
    76.2 3038.92      87 3036.19    92.6 3033.64   116.1 3031.06   136.1 3030.39
   148.1 3027.66   160.1 3027.33   185.4 3020.49   205.8 3018.99   213.1  3016.9
   223.1 3015.83   231.7  3016.7   243.7 3020.57   249.9 3021.46   271.3 3022.44
   332.3 3023.08   384.3 3023.09   407.6 3024.94   463.3 3025.25   547.3 3026.16
   563.3 3026.99   575.3  3028.2   583.3 3030.42   594.8 3032.36   606.3 3035.85
#Mann= 7 ,-1,0
       0      .1       0      62     .06       0   213.1    .045       0
   231.7      .1       0   332.3     .06       0   463.3     .12       0
   563.3      .1       0
#XS Ineff= 2 , 0
             203  3025.7     242          3025.8
Permanent Ineff=
       F       F
Bank Sta=213.1,231.7
XS Rating Curve= 0 ,0
Exp/Cntr(USF)=0,0
Exp/Cntr=0.5,0.3

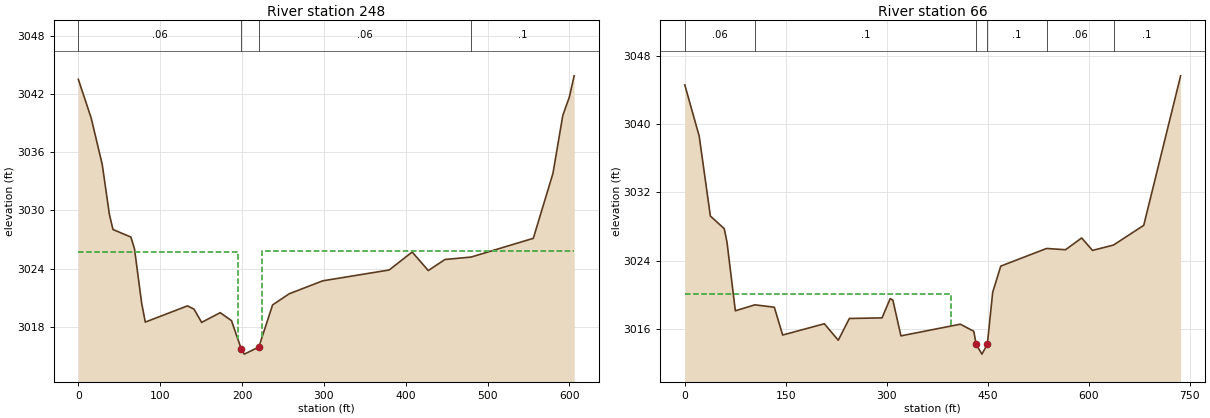
Type RM Length L Ch R = 1 ,248     ,181.7,181.7,181.7
BEGIN DESCRIPTION:
Structure XS 2; 12.1 ft between structure
END DESCRIPTION:
XS GIS Cut Line= 6
2313722.81591321617654.7659797052313638.25381501617692.549044859
 2313639.1534118617783.4083205862313598.67155628617882.363967417
 2313529.4026035617934.5405812012313524.90461955618163.038165702
#Sta/Elev= 30
       0  3043.5    15.7 3039.51    29.2 3034.73    37.9 3029.61    42.3 3028.03
    64.2 3027.25    68.6 3026.04    77.4 3020.42    81.8 3018.49   133.3 3020.16
   141.3 3019.83   150.6 3018.46   173.3 3019.46   187.1 3018.64     199 3015.73
   202.7 3015.19   220.53015.917   237.3 3020.26   257.7 3021.41   298.5 3022.74
   379.8 3023.86   407.8 3025.71   427.5  3023.8   447.9 3024.94   479.8 3025.19
   555.8 3027.12   579.8 3033.81   591.8 3039.77   599.8 3041.67   605.7 3043.86
#Mann= 4 ,-1,0
       0     .06       0     199    .045       0   220.5     .06       0
   479.8      .1       0
#XS Ineff= 2 , 0
             195  3025.7   224.5          3025.8
Permanent Ineff=
       F       F
Bank Sta=199,220.5
XS Rating Curve= 0 ,0
Exp/Cntr(USF)=0,0
Exp/Cntr=0.5,0.3

Type RM Length L Ch R = 1 ,66      ,,,
BEGIN DESCRIPTION:
Structure XS 1
END DESCRIPTION:
XS GIS Cut Line= 3
2313724.92399279 617610.878626792313447.65153151617682.481954706
2313475.07408262618131.907098003
#Sta/Elev= 30
       0 3044.61    21.4  3038.6      38 3029.23    58.6 3027.75    62.7 3026.17
    75.1 3018.12   104.1 3018.82     133 3018.54   145.4 3015.28   207.3  3016.6
     228 3014.67   244.5 3017.22     293 3017.29   305.1 3019.54   309.1 3019.38
   321.1 3015.18   409.3 3016.55   429.3 3015.72   432.9 3014.18   441.4 3013.04
   449.4 3014.18   457.4 3020.29   469.4 3023.36   537.5 3025.43   565.6 3025.28
   589.6 3026.66   605.7  3025.2   636.9 3025.83   681.8 3028.14   736.6 3045.67
#Mann= 6 ,-1,0
       0     .06       0   104.1      .1       0   432.9    .045       0
   449.4      .1       0   537.5     .06       0   636.9      .1       0
#XS Ineff= 2 , 0
          396.17 3020.04
Permanent Ineff=
       F       F
Bank Sta=432.9,449.4
XS Rating Curve= 0 ,0
Exp/Cntr(USF)=0,0
Exp/Cntr=0.3,0.1
LCMann Table=0

Chan Stop Cuts=-1
Use User Specified Reach Order=0
Composite Channel Slope=5